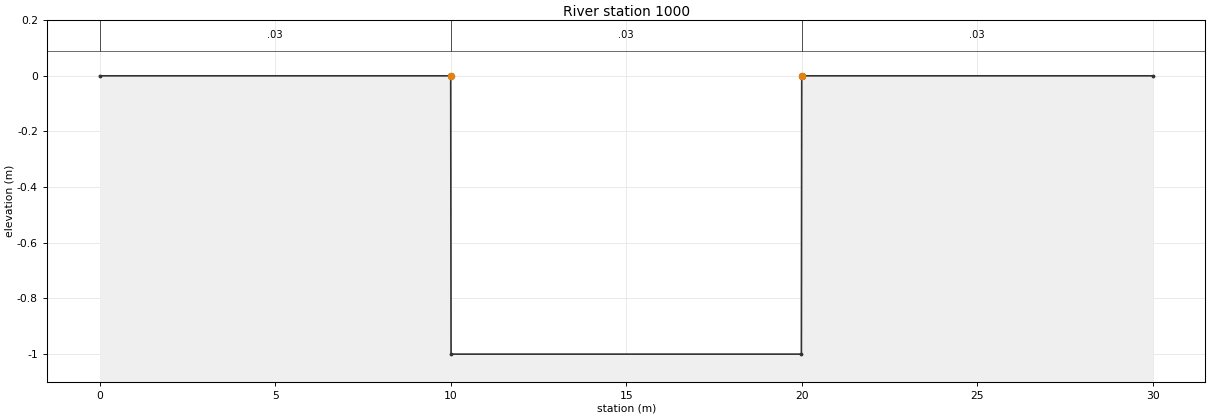
--- ras_bridge.prj (project) ---

Proj Title=ras_bridge
Current Plan=p01
Default Exp/Contr=0.3,0.1
SI Units
Geom File=g01
Unsteady File=u01
Plan File=p01
Y Axis Title=Elevation
X Axis Title(PF)=Main Channel Distance
X Axis Title(XS)=Station
BEGIN DESCRIPTION:
END DESCRIPTION:
DSS Start Date=22SEP2008
DSS Start Time=00:00
DSS End Date=22SEP2008
DSS End Time=04:00
DSS File=dss
DSS Export Rating Curves= 0
DSS Export Rating Curve Sorted= 0
DSS Export Volume Flow Curves= 0
DXF OffsetX= 0
DXF OffsetY= 0
DXF ScaleX= 1
DXF ScaleY= 10

--- ras_bridge.p01 (plan) ---

Plan Title=ras_bridge_plan
Program Version=4.10
Short Identifier=ras_bridge_plan
Simulation Date=22SEP2008,00:00,22SEP2008,05:00
Geom File=g01
Flow File=u01
Subcritical Flow
K Sum by GR= 0
Std Step Tol= 0.003
Critical Tol= 0.003
Num of Std Step Trials= 20
Max Error Tol= 0.1
Flow Tol Ratio= 0.001
Split Flow NTrial= 30
Split Flow Tol= 0.006
Split Flow Ratio= 0.02
Log Output Level= 0
Friction Slope Method= 1
Unsteady Friction Slope Method= 2
Unsteady Bridges Friction Slope Method= 1
Parabolic Critical Depth
Global Vel Dist= 0 , 0 , 0
Global Log Level= 0
CheckData=True
Encroach Param=-1 ,0,0, 0
Computation Interval=1MIN
Output Interval=1MIN
Run HTab= 1
Run UNet= 1
Run PostProcess= 1
Run WQNet= 0
UNET Theta= 1
UNET Theta Warmup= 1
UNET ZTol= 0.006
UNET ZSATol= 0.015
UNET MxIter= 20
UNET MaxInSteps= 0
UNET DtIC= 0
UNET DtMin= 0
UNET MaxCRTS= 20
UNET WFStab= 2
UNET SFStab= 1
UNET WFX= 1
UNET SFX= 1
UNET DSS MLevel= 4
UNET DZMax Abort= 30
UNET Convert EG Bridges= 0
UNET Use Existing IB Tables=-1
UNET Froude Reduction=True
UNET Froude Limit= 1
UNET Froude Power= 10
UNET Time Slicing=0,0, 5
UNET Junction Losses=0
Instantaneous Interval=1MIN
DSS File=dss
Write IC File= 0
Write IC File at Sim End=0
Echo Input=False
Echo Parameters=False
Echo Output=False
Write Detailed= 0
Stage Flow Hydrograph=river1          ,reach1          ,1000
Stage Flow Hydrograph=river1          ,reach1          ,975.*
Stage Flow Hydrograph=river1          ,reach1          ,950.*
Stage Flow Hydrograph=river1          ,reach1          ,925.*
Stage Flow Hydrograph=river1          ,reach1          ,900.*
Stage Flow Hydrograph=river1          ,reach1          ,875.*
Stage Flow Hydrograph=river1          ,reach1          ,850.*
Stage Flow Hydrograph=river1          ,reach1          ,825.*
Stage Flow Hydrograph=river1          ,reach1          ,800.*
Stage Flow Hydrograph=river1          ,reach1          ,775.*
Stage Flow Hydrograph=river1          ,reach1          ,750.*
Stage Flow Hydrograph=river1          ,reach1          ,725.*
Stage Flow Hydrograph=river1          ,reach1          ,700.*
Stage Flow Hydrograph=river1          ,reach1          ,675.*
Stage Flow Hydrograph=river1          ,reach1          ,650.*
Stage Flow Hydrograph=river1          ,reach1          ,625.*
Stage Flow Hydrograph=river1          ,reach1          ,600.*
Stage Flow Hydrograph=river1          ,reach1          ,575.*
Stage Flow Hydrograph=river1          ,reach1          ,550.*
Stage Flow Hydrograph=river1          ,reach1          ,525.*
Stage Flow Hydrograph=river1          ,reach1          ,475.*
Stage Flow Hydrograph=river1          ,reach1          ,450.*
Stage Flow Hydrograph=river1          ,reach1          ,425.*
Stage Flow Hydrograph=river1          ,reach1          ,400.*
Stage Flow Hydrograph=river1          ,reach1          ,375.*
Stage Flow Hydrograph=river1          ,reach1          ,350.*
Stage Flow Hydrograph=river1          ,reach1          ,325.*
Stage Flow Hydrograph=river1          ,reach1          ,300.*
Stage Flow Hydrograph=river1          ,reach1          ,275.*
Stage Flow Hydrograph=river1          ,reach1          ,250.*
Stage Flow Hydrograph=river1          ,reach1          ,225.*
Stage Flow Hydrograph=river1          ,reach1          ,200.*
Stage Flow Hydrograph=river1          ,reach1          ,175.*
Stage Flow Hydrograph=river1          ,reach1          ,150.*
Stage Flow Hydrograph=river1          ,reach1          ,125.*
Stage Flow Hydrograph=river1          ,reach1          ,100.*
Stage Flow Hydrograph=river1          ,reach1          ,74.9999*
Stage Flow Hydrograph=river1          ,reach1          ,50.0000*
Stage Flow Hydrograph=river1          ,reach1          ,24.9999*
Stage Flow Hydrograph=river1          ,reach1          ,0
WQ AD Non Conservative
WQ ULTIMATE=-1
WQ Max Comp Step=1HOUR
WQ Output Interval=15MIN
WQ Output Selected Increments= 0
WQ Output face flow=0
WQ Output face velocity=0
WQ Output face area=0
WQ Output face dispersion=0
WQ Output cell volume=0
WQ Output cell surface area=0
WQ Output cell continuity=0
WQ Output cumulative cell continuity=0
WQ Output face conc=0
WQ Output face dconc_dx=0
WQ Output face courant=0
WQ Output face peclet=0
WQ Output face adv mass=0
WQ Output face disp mass=0
WQ Output cell mass=0
WQ Output cell source sink temp=0
WQ Output cell source sink nsm=0
WQ Output MaxMinRange=-1
WQ Daily Max Min Mean=-1
WQ Daily Range=0
WQ Daily Time=0
WQ Create Restart=0
WQ Fixed Restart=0
WQ System Summary=0
WQ Use Fixed Temperature=0
Sorting and Armoring Iterations= 10
XS Update Threshold= 0.02
Hydraulics Update Threshold= 0.02
Energy Slope Method= 1
Volume Change Method= 0
XS Weighting Method= 0
Number of US Weighted Cross Sections= 1
Number of DS Weighted Cross Sections= 1
Upstream XS Weight=0.25
Main XS Weight=0.5
Downstream XS Weight=0.25
Number of DS XS's Weighted with US Boundary= 1
Upstream Boundary Weight= 1
Weight of XSs Associated with US Boundary= 0
Number of US XS's Weighted with DS Boundary= 1
Downstream Boundary Weight= 0.5
Weight of XSs Associated with DS Boundary= 0.5
Sediment Output Level= 4
Mass or Volume Output= 0
Output Increment Type= 1
Profile and TS Output Increment= 10
XS Output Flag= 0
XS Output Increment= 10
Disregard all LS=0
Disregard all Conn=0
Disregard all Breaches=0
Disregard all Pumps=0

--- ras_bridge.u01 (unsteady flow) ---

Flow Title=ras_bridge_unsteady
Program Version=4.10
Use Restart= 0
Boundary Location=river1          ,reach1          ,1000    ,        ,                ,                ,
Interval=5MIN
Flow Hydrograph= 61
       3       3       3       3       3       3       4       5       6       6
       6       6       6       7       8       9      10      10      10      10
      10      11      12      13      14      15      15      15      15      16
      17      18      19      20      21      23      25      30      35      40
      45      50      55      60      65      70      70      70      70      70
      70      70      70      70      70      70      70      70      70      70
      70
Use DSS=False
CWMS InputPosition= 0
Use Fixed Start Time=False
Is Critical Boundary=False
Boundary Location=river1          ,reach1          ,0       ,        ,                ,                ,
Friction Slope=0.005

--- ras_bridge.g01 (geometry) ---

Geom Title=ras_bridge_geo
Program Version=4.10

River Reach=river1          ,reach1
Reach XY= 2
 0.42060085836910.894849785407730.42489270386266 0.1137339055794

Type RM Length L Ch R = 1 ,1000    ,25,25,25
#Sta/Elev= 6
       0       0      10       0   10.01      -1   19.99      -1      20       0
      30       0
#Mann= 3 , 0 , 0
       0     .03       0      10     .03       0      20     .03       0
Bank Sta=10,20
XS Rating Curve= 0 ,0
Exp/Cntr=0.3,0.1

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