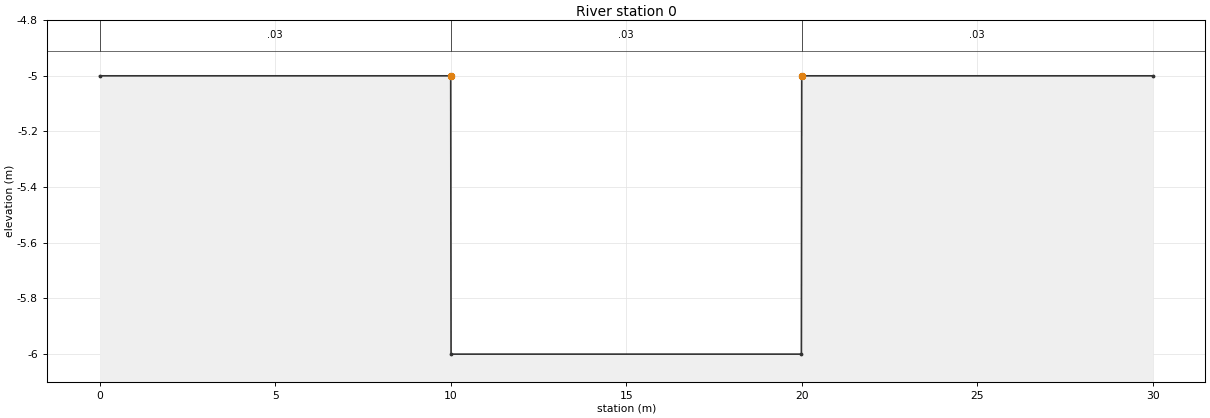
HEC-RAS study ras_bridge.prj: ras_bridge

--- ras_bridge.g01 (geometry) --- (continued)

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
Type RM Length L Ch R = 1 ,0       ,0,0,0
#Sta/Elev= 6
       0      -5      10      -5   10.01      -6   19.99      -6      20      -5
      30      -5
#Mann= 3 , 0 , 0
       0     .03       0      10     .03       0      20     .03       0
Bank Sta=10,20
XS Rating Curve= 0 ,0
Exp/Cntr=0.3,0.1

Chan Stop Cuts=-1
Use User Specified Reach Order=0
Composite Channel Slope=5