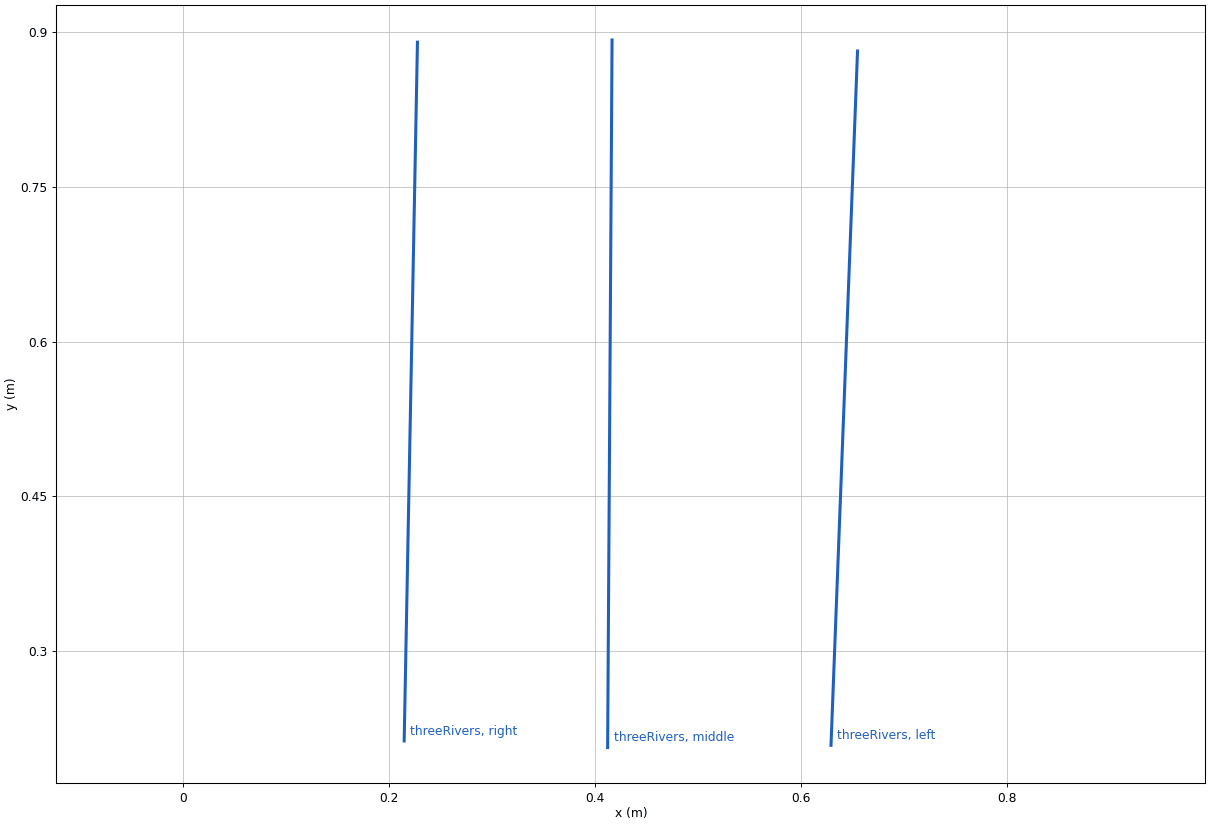
--- riverwall_ANUGA.prj (project) ---

Proj Title=riverwall_ANUGA
Current Plan=p01
Default Exp/Contr=0.3,0.1
SI Units
Geom File=g01
Unsteady File=u01
Plan File=p01
Y Axis Title=Elevation
X Axis Title(PF)=Main Channel Distance
X Axis Title(XS)=Station
BEGIN DESCRIPTION:
END DESCRIPTION:
DSS File=dss
DSS Export Rating Curves= 0
DSS Export Rating Curve Sorted= 0
DSS Export Volume Flow Curves= 0
DXF OffsetX= 0
DXF OffsetY= 0
DXF ScaleX= 1
DXF ScaleY= 10

--- riverwall_ANUGA.p01 (plan) ---

Plan Title=riverwall_ANUGA
Program Version=4.10
Short Identifier=riverwall_ANUGA
Simulation Date=22SEP2008,00:00,22SEP2008,24:00
Geom File=g01
Flow File=u01
Subcritical Flow
K Sum by GR= 0
Std Step Tol= 0.003
Critical Tol= 0.003
Num of Std Step Trials= 20
Max Error Tol= 0.1
Flow Tol Ratio= 0.001
Split Flow NTrial= 30
Split Flow Tol= 0.006
Split Flow Ratio= 0.02
Log Output Level= 0
Friction Slope Method= 1
Unsteady Friction Slope Method= 2
Unsteady Bridges Friction Slope Method= 1
Parabolic Critical Depth
Global Vel Dist= 0 , 0 , 0
Global Log Level= 0
CheckData=True
Encroach Param=-1 ,0,0, 0
Computation Interval=3SEC
Output Interval=5MIN
Run HTab= 1
Run UNet= 1
Run PostProcess= 1
Run WQNet= 0
UNET Theta= 1
UNET Theta Warmup= 1
UNET ZTol= 0.006
UNET ZSATol= 0.015
UNET MxIter= 20
UNET MaxInSteps= 0
UNET DtIC= 0
UNET DtMin= 0
UNET MaxCRTS= 20
UNET WFStab= 2
UNET SFStab= 1
UNET WFX= 1
UNET SFX= 1
UNET DSS MLevel= 4
UNET DZMax Abort= 30
UNET Convert EG Bridges= 0
UNET Use Existing IB Tables=-1
UNET Froude Reduction=True
UNET Froude Limit= 1
UNET Froude Power= 10
UNET Time Slicing=0,0, 5
UNET Junction Losses=0
Instantaneous Interval=5MIN
DSS File=dss
Write IC File= 0
Write IC File at Sim End=0
Echo Input=False
Echo Parameters=False
Echo Output=False
Write Detailed= 0
Stage Flow Hydrograph=threeRivers     ,middle          ,1000
Stage Flow Hydrograph=threeRivers     ,middle          ,983.333*
Stage Flow Hydrograph=threeRivers     ,middle          ,966.666*
Stage Flow Hydrograph=threeRivers     ,middle          ,950.*
Stage Flow Hydrograph=threeRivers     ,middle          ,933.333*
Stage Flow Hydrograph=threeRivers     ,middle          ,916.666*
Stage Flow Hydrograph=threeRivers     ,middle          ,900.*
Stage Flow Hydrograph=threeRivers     ,middle          ,883.333*
Stage Flow Hydrograph=threeRivers     ,middle          ,866.666*
Stage Flow Hydrograph=threeRivers     ,middle          ,850.*
Stage Flow Hydrograph=threeRivers     ,middle          ,833.333*
Stage Flow Hydrograph=threeRivers     ,middle          ,816.666*
Stage Flow Hydrograph=threeRivers     ,middle          ,800.*
Stage Flow Hydrograph=threeRivers     ,middle          ,783.333*
Stage Flow Hydrograph=threeRivers     ,middle          ,766.666*
Stage Flow Hydrograph=threeRivers     ,middle          ,750.*
Stage Flow Hydrograph=threeRivers     ,middle          ,733.333*
Stage Flow Hydrograph=threeRivers     ,middle          ,716.666*
Stage Flow Hydrograph=threeRivers     ,middle          ,700.*
Stage Flow Hydrograph=threeRivers     ,middle          ,683.333*
Stage Flow Hydrograph=threeRivers     ,middle          ,666.666*
Stage Flow Hydrograph=threeRivers     ,middle          ,650.*
Stage Flow Hydrograph=threeRivers     ,middle          ,633.333*
Stage Flow Hydrograph=threeRivers     ,middle          ,616.666*
Stage Flow Hydrograph=threeRivers     ,middle          ,600.*
Stage Flow Hydrograph=threeRivers     ,middle          ,583.333*
Stage Flow Hydrograph=threeRivers     ,middle          ,566.666*
Stage Flow Hydrograph=threeRivers     ,middle          ,550.*
Stage Flow Hydrograph=threeRivers     ,middle          ,533.333*
Stage Flow Hydrograph=threeRivers     ,middle          ,516.666*
Stage Flow Hydrograph=threeRivers     ,middle          ,500.*
Stage Flow Hydrograph=threeRivers     ,middle          ,483.333*
Stage Flow Hydrograph=threeRivers     ,middle          ,466.666*
Stage Flow Hydrograph=threeRivers     ,middle          ,450.*
Stage Flow Hydrograph=threeRivers     ,middle          ,433.333*
Stage Flow Hydrograph=threeRivers     ,middle          ,416.666*
Stage Flow Hydrograph=threeRivers     ,middle          ,400.*
Stage Flow Hydrograph=threeRivers     ,middle          ,383.333*
Stage Flow Hydrograph=threeRivers     ,middle          ,366.666*
Stage Flow Hydrograph=threeRivers     ,middle          ,350.*
Stage Flow Hydrograph=threeRivers     ,middle          ,333.333*
Stage Flow Hydrograph=threeRivers     ,middle          ,316.666*
Stage Flow Hydrograph=threeRivers     ,middle          ,300.*
Stage Flow Hydrograph=threeRivers     ,middle          ,283.333*
Stage Flow Hydrograph=threeRivers     ,middle          ,266.666*
Stage Flow Hydrograph=threeRivers     ,middle          ,250.*
Stage Flow Hydrograph=threeRivers     ,middle          ,233.333*
Stage Flow Hydrograph=threeRivers     ,middle          ,216.666*
Stage Flow Hydrograph=threeRivers     ,middle          ,200.*
Stage Flow Hydrograph=threeRivers     ,middle          ,183.333*
Stage Flow Hydrograph=threeRivers     ,middle          ,166.666*
Stage Flow Hydrograph=threeRivers     ,middle          ,150.*
Stage Flow Hydrograph=threeRivers     ,middle          ,133.333*
Stage Flow Hydrograph=threeRivers     ,middle          ,116.666*
Stage Flow Hydrograph=threeRivers     ,middle          ,100.*
Stage Flow Hydrograph=threeRivers     ,middle          ,83.3333*
Stage Flow Hydrograph=threeRivers     ,middle          ,66.6666*
Stage Flow Hydrograph=threeRivers     ,middle          ,50.0000*
Stage Flow Hydrograph=threeRivers     ,middle          ,33.3333*
Stage Flow Hydrograph=threeRivers     ,middle          ,16.6666*
Stage Flow Hydrograph=threeRivers     ,middle          ,0
Stage Flow Hydrograph=threeRivers     ,right           ,1000
Stage Flow Hydrograph=threeRivers     ,right           ,983.333*
Stage Flow Hydrograph=threeRivers     ,right           ,966.666*
Stage Flow Hydrograph=threeRivers     ,right           ,950.*
Stage Flow Hydrograph=threeRivers     ,right           ,933.333*
Stage Flow Hydrograph=threeRivers     ,right           ,916.666*
Stage Flow Hydrograph=threeRivers     ,right           ,900.*
Stage Flow Hydrograph=threeRivers     ,right           ,883.333*
Stage Flow Hydrograph=threeRivers     ,right           ,866.666*
Stage Flow Hydrograph=threeRivers     ,right           ,850.*
Stage Flow Hydrograph=threeRivers     ,right           ,833.333*
Stage Flow Hydrograph=threeRivers     ,right           ,816.666*
Stage Flow Hydrograph=threeRivers     ,right           ,800.*
Stage Flow Hydrograph=threeRivers     ,right           ,783.333*
Stage Flow Hydrograph=threeRivers     ,right           ,766.666*
Stage Flow Hydrograph=threeRivers     ,right           ,750.*
Stage Flow Hydrograph=threeRivers     ,right           ,733.333*
Stage Flow Hydrograph=threeRivers     ,right           ,716.666*
Stage Flow Hydrograph=threeRivers     ,right           ,700.*
Stage Flow Hydrograph=threeRivers     ,right           ,683.333*
Stage Flow Hydrograph=threeRivers     ,right           ,666.666*
Stage Flow Hydrograph=threeRivers     ,right           ,650.*
Stage Flow Hydrograph=threeRivers     ,right           ,633.333*
Stage Flow Hydrograph=threeRivers     ,right           ,616.666*
Stage Flow Hydrograph=threeRivers     ,right           ,600.*
Stage Flow Hydrograph=threeRivers     ,right           ,583.333*
Stage Flow Hydrograph=threeRivers     ,right           ,566.666*
Stage Flow Hydrograph=threeRivers     ,right           ,550.*
Stage Flow Hydrograph=threeRivers     ,right           ,533.333*
Stage Flow Hydrograph=threeRivers     ,right           ,516.666*
Stage Flow Hydrograph=threeRivers     ,right           ,500.*
Stage Flow Hydrograph=threeRivers     ,right           ,483.333*
Stage Flow Hydrograph=threeRivers     ,right           ,466.666*
Stage Flow Hydrograph=threeRivers     ,right           ,450.*
Stage Flow Hydrograph=threeRivers     ,right           ,433.333*
Stage Flow Hydrograph=threeRivers     ,right           ,416.666*
Stage Flow Hydrograph=threeRivers     ,right           ,400.*
Stage Flow Hydrograph=threeRivers     ,right           ,383.333*
Stage Flow Hydrograph=threeRivers     ,right           ,366.666*
Stage Flow Hydrograph=threeRivers     ,right           ,350.*
Stage Flow Hydrograph=threeRivers     ,right           ,333.333*
Stage Flow Hydrograph=threeRivers     ,right           ,316.666*
Stage Flow Hydrograph=threeRivers     ,right           ,300.*
Stage Flow Hydrograph=threeRivers     ,right           ,283.333*
Stage Flow Hydrograph=threeRivers     ,right           ,266.666*
Stage Flow Hydrograph=threeRivers     ,right           ,250.*
Stage Flow Hydrograph=threeRivers     ,right           ,233.333*
Stage Flow Hydrograph=threeRivers     ,right           ,216.666*
Stage Flow Hydrograph=threeRivers     ,right           ,200.*
Stage Flow Hydrograph=threeRivers     ,right           ,183.333*
Stage Flow Hydrograph=threeRivers     ,right           ,166.666*
Stage Flow Hydrograph=threeRivers     ,right           ,150.*
Stage Flow Hydrograph=threeRivers     ,right           ,133.333*
Stage Flow Hydrograph=threeRivers     ,right           ,116.666*
Stage Flow Hydrograph=threeRivers     ,right           ,100.*
Stage Flow Hydrograph=threeRivers     ,right           ,83.3333*
Stage Flow Hydrograph=threeRivers     ,right           ,66.6666*
Stage Flow Hydrograph=threeRivers     ,right           ,50.0000*
Stage Flow Hydrograph=threeRivers     ,right           ,33.3333*
Stage Flow Hydrograph=threeRivers     ,right           ,16.6666*
Stage Flow Hydrograph=threeRivers     ,right           ,0
Stage Flow Hydrograph=threeRivers     ,left            ,1000
Stage Flow Hydrograph=threeRivers     ,left            ,983.333*
Stage Flow Hydrograph=threeRivers     ,left            ,966.666*
Stage Flow Hydrograph=threeRivers     ,left            ,950.*
Stage Flow Hydrograph=threeRivers     ,left            ,933.333*
Stage Flow Hydrograph=threeRivers     ,left            ,916.666*
Stage Flow Hydrograph=threeRivers     ,left            ,900.*
Stage Flow Hydrograph=threeRivers     ,left            ,883.333*
Stage Flow Hydrograph=threeRivers     ,left            ,866.666*
Stage Flow Hydrograph=threeRivers     ,left            ,850.*
Stage Flow Hydrograph=threeRivers     ,left            ,833.333*
Stage Flow Hydrograph=threeRivers     ,left            ,816.666*
Stage Flow Hydrograph=threeRivers     ,left            ,800.*
Stage Flow Hydrograph=threeRivers     ,left            ,783.333*
Stage Flow Hydrograph=threeRivers     ,left            ,766.666*
Stage Flow Hydrograph=threeRivers     ,left            ,750.*
Stage Flow Hydrograph=threeRivers     ,left            ,733.333*
Stage Flow Hydrograph=threeRivers     ,left            ,716.666*
Stage Flow Hydrograph=threeRivers     ,left            ,700.*
Stage Flow Hydrograph=threeRivers     ,left            ,683.333*
Stage Flow Hydrograph=threeRivers     ,left            ,666.666*
Stage Flow Hydrograph=threeRivers     ,left            ,650.*
Stage Flow Hydrograph=threeRivers     ,left            ,633.333*
Stage Flow Hydrograph=threeRivers     ,left            ,616.666*
Stage Flow Hydrograph=threeRivers     ,left            ,600.*
Stage Flow Hydrograph=threeRivers     ,left            ,583.333*
Stage Flow Hydrograph=threeRivers     ,left            ,566.666*
Stage Flow Hydrograph=threeRivers     ,left            ,550.*
Stage Flow Hydrograph=threeRivers     ,left            ,533.333*
Stage Flow Hydrograph=threeRivers     ,left            ,516.666*
Stage Flow Hydrograph=threeRivers     ,left            ,500.*
Stage Flow Hydrograph=threeRivers     ,left            ,483.333*
Stage Flow Hydrograph=threeRivers     ,left            ,466.666*
Stage Flow Hydrograph=threeRivers     ,left            ,450.*
Stage Flow Hydrograph=threeRivers     ,left            ,433.333*
Stage Flow Hydrograph=threeRivers     ,left            ,416.666*
Stage Flow Hydrograph=threeRivers     ,left            ,400.*
Stage Flow Hydrograph=threeRivers     ,left            ,383.333*
Stage Flow Hydrograph=threeRivers     ,left            ,366.666*
Stage Flow Hydrograph=threeRivers     ,left            ,350.*
Stage Flow Hydrograph=threeRivers     ,left            ,333.333*
Stage Flow Hydrograph=threeRivers     ,left            ,316.666*
Stage Flow Hydrograph=threeRivers     ,left            ,300.*
Stage Flow Hydrograph=threeRivers     ,left            ,283.333*
Stage Flow Hydrograph=threeRivers     ,left            ,266.666*
Stage Flow Hydrograph=threeRivers     ,left            ,250.*
Stage Flow Hydrograph=threeRivers     ,left            ,233.333*
Stage Flow Hydrograph=threeRivers     ,left            ,216.666*
Stage Flow Hydrograph=threeRivers     ,left            ,200.*
Stage Flow Hydrograph=threeRivers     ,left            ,183.333*
Stage Flow Hydrograph=threeRivers     ,left            ,166.666*
Stage Flow Hydrograph=threeRivers     ,left            ,150.*
Stage Flow Hydrograph=threeRivers     ,left            ,133.333*
Stage Flow Hydrograph=threeRivers     ,left            ,116.666*
Stage Flow Hydrograph=threeRivers     ,left            ,100.*
Stage Flow Hydrograph=threeRivers     ,left            ,83.3333*
Stage Flow Hydrograph=threeRivers     ,left            ,66.6666*
Stage Flow Hydrograph=threeRivers     ,left            ,50.0000*
Stage Flow Hydrograph=threeRivers     ,left            ,33.3333*
Stage Flow Hydrograph=threeRivers     ,left            ,16.6666*
Stage Flow Hydrograph=threeRivers     ,left            ,0
WQ AD Non Conservative
WQ ULTIMATE=-1
WQ Max Comp Step=1HOUR
WQ Output Interval=15MIN
WQ Output Selected Increments= 0
WQ Output face flow=0
WQ Output face velocity=0
WQ Output face area=0
WQ Output face dispersion=0
WQ Output cell volume=0
WQ Output cell surface area=0
WQ Output cell continuity=0
WQ Output cumulative cell continuity=0
WQ Output face conc=0
WQ Output face dconc_dx=0
WQ Output face courant=0
WQ Output face peclet=0
WQ Output face adv mass=0
WQ Output face disp mass=0
WQ Output cell mass=0
WQ Output cell source sink temp=0
WQ Output cell source sink nsm=0
WQ Output MaxMinRange=-1
WQ Daily Max Min Mean=-1
WQ Daily Range=0
WQ Daily Time=0
WQ Create Restart=0
WQ Fixed Restart=0
WQ System Summary=0
WQ Use Fixed Temperature=0
Sorting and Armoring Iterations= 10
XS Update Threshold= 0.02
Hydraulics Update Threshold= 0.02
Energy Slope Method= 1
Volume Change Method= 0
XS Weighting Method= 0
Number of US Weighted Cross Sections= 1
Number of DS Weighted Cross Sections= 1
Upstream XS Weight=0.25
Main XS Weight=0.5
Downstream XS Weight=0.25
Number of DS XS's Weighted with US Boundary= 1
Upstream Boundary Weight= 1
Weight of XSs Associated with US Boundary= 0
Number of US XS's Weighted with DS Boundary= 1
Downstream Boundary Weight= 0.5
Weight of XSs Associated with DS Boundary= 0.5
Sediment Output Level= 4
Mass or Volume Output= 0
Output Increment Type= 1
Profile and TS Output Increment= 10
XS Output Flag= 0
XS Output Increment= 10
Disregard all LS=0
Disregard all Conn=0
Disregard all Breaches=0
Disregard all Pumps=0

--- riverwall_ANUGA.u01 (unsteady flow) ---

Flow Title=riverwall_ANUGA
Program Version=4.10
Use Restart= 0
Initial Flow Loc=threeRivers     ,middle          ,1000    ,1
Initial Flow Loc=threeRivers     ,right           ,1000    ,1
Initial Flow Loc=threeRivers     ,left            ,1000    ,1
Boundary Location=threeRivers     ,middle          ,1000    ,        ,                ,                ,
Interval=1HOUR
Flow Hydrograph= 25
       1       1       5       9      13      17      21      21      21      21
      21      21      21      21      21      21      21      21      21      21
      21      21      21      21      21
Flow Hydrograph QMin= 1
Use DSS=False
CWMS InputPosition= 0
Use Fixed Start Time=False
Is Critical Boundary=False
Boundary Location=threeRivers     ,middle          ,0       ,        ,                ,                ,
Friction Slope=0.003
Boundary Location=threeRivers     ,right           ,1000    ,        ,                ,                ,
Interval=1HOUR
Flow Hydrograph= 25
       1       1       1       1       1       1       1       1       1       1
       1       1       1       1       1       1       1       1       1       1
       1       1       1       1       1
Flow Hydrograph QMin= 0.1
Flow Hydrograph QMult= 0.1
Use DSS=False
CWMS InputPosition= 0
Use Fixed Start Time=False
Is Critical Boundary=False
Boundary Location=threeRivers     ,right           ,0       ,        ,                ,                ,
Friction Slope=0.003
Boundary Location=threeRivers     ,left            ,1000    ,        ,                ,                ,
Interval=1HOUR
Flow Hydrograph= 25
       1       1       1       1       1       1       1       1       1       1
       1       1       1       1       1       1       1       1       1       1
       1       1       1       1       1
Flow Hydrograph QMin= 0.1
Flow Hydrograph QMult= 0.1
Use DSS=False
CWMS InputPosition= 0
Use Fixed Start Time=False
Is Critical Boundary=False
Boundary Location=threeRivers     ,left            ,0       ,        ,                ,                ,
Friction Slope=0.003

--- riverwall_ANUGA.g01 (geometry) ---

Geom Title=riverwall_ANGUA
Program Version=4.10

River Reach=threeRivers     ,left
Reach XY= 2
0.654506437768240.881974248927040.628755364806870.20815450643777

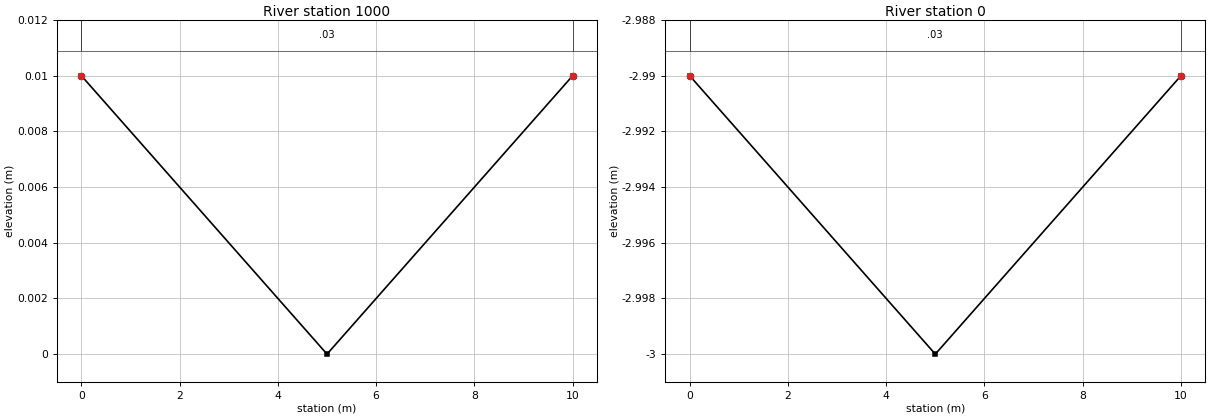
Type RM Length L Ch R = 1 ,1000    ,16.667,16.667,16.667
#Sta/Elev= 3
       0     .01       5       0      10     .01
#Mann= 3 , 0 , 0
       0     .03       0       0     .03       0      10     .03       0
Bank Sta=0,10
XS Rating Curve= 0 ,0
Exp/Cntr=0.3,0.1

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
Type RM Length L Ch R = 1 ,0       ,1000,1000,1000
#Sta/Elev= 3
       0   -2.99       5      -3      10   -2.99
#Mann= 3 , 0 , 0
       0     .03       0       0     .03       0      10     .03       0
Bank Sta=0,10
XS Rating Curve= 0 ,0
Exp/Cntr=0.3,0.1

River Reach=threeRivers     ,right
Reach XY= 2
 0.22746781115880.890557939914160.214592274678110.21244635193133

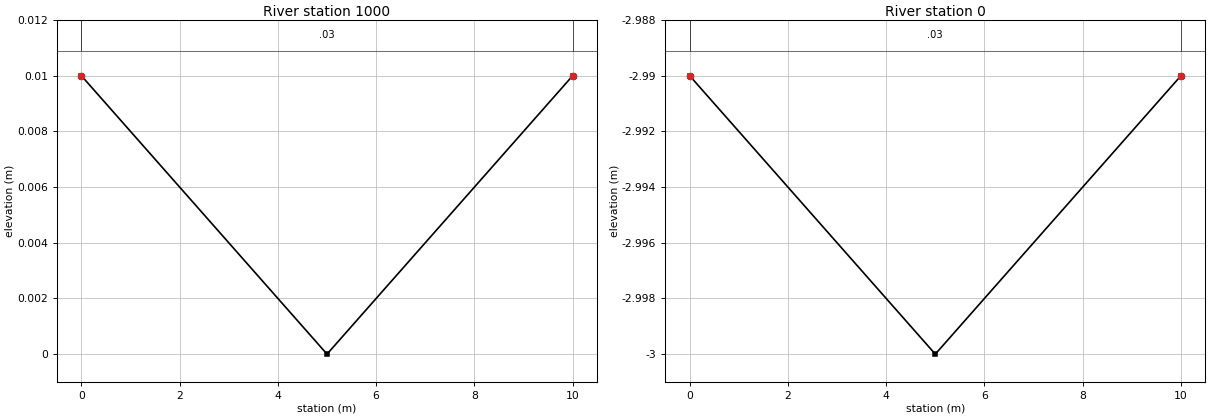
Type RM Length L Ch R = 1 ,1000    ,16.667,16.667,16.667
#Sta/Elev= 3
       0     .01       5       0      10     .01
#Mann= 3 , 0 , 0
       0     .03       0       0     .03       0      10     .03       0
Bank Sta=0,10
XS Rating Curve= 0 ,0
Exp/Cntr=0.3,0.1

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
Type RM Length L Ch R = 1 ,0       ,0,0,0
#Sta/Elev= 3
       0   -2.99       5      -3      10   -2.99
#Mann= 3 , 0 , 0
       0     .03       0       0     .03       0      10     .03       0
Bank Sta=0,10
XS Rating Curve= 0 ,0
Exp/Cntr=0.3,0.1

River Reach=threeRivers     ,middle
Reach XY= 2
0.416309012875540.892703862660940.412017167381970.20600858369099

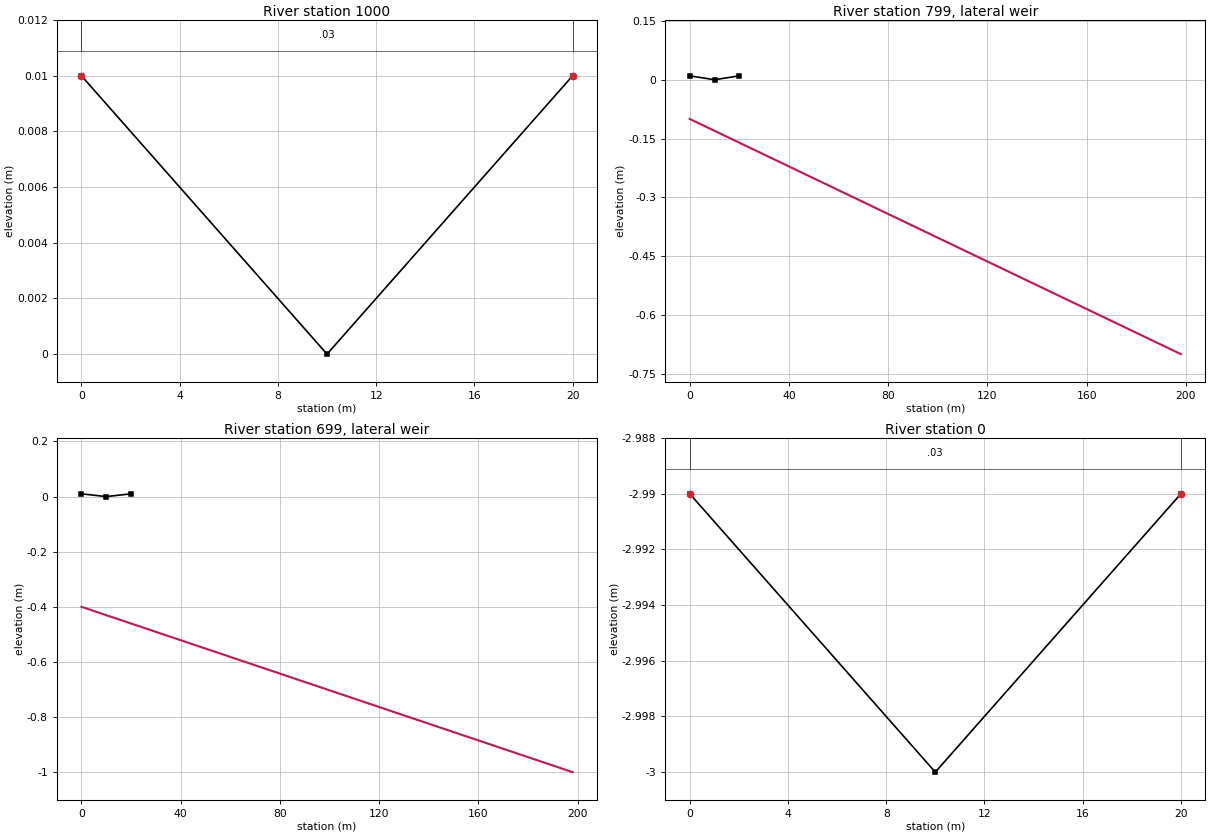
Type RM Length L Ch R = 1 ,1000    ,16.667,16.667,16.667
#Sta/Elev= 3
       0     .01      10       0      20     .01
#Mann= 3 , 0 , 0
       0     .03       0       0     .03       0      20     .03       0
Bank Sta=0,20
XS Rating Curve= 0 ,0
Exp/Cntr=0.3,0.1

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
Type RM Length L Ch R = 6 ,799     ,,,
Lateral Weir Pos= 3
Lateral Weir End=threeRivers     ,right           ,800.*   ,
Lateral Weir Distance=1
Lateral Weir TW Multiple XS=-1
Lateral Weir WD=1
Lateral Weir Coef=1.1
Lateral Weir WSCriteria=-1
Lateral Weir Flap Gates= 0
Lateral Weir Hagers EQN= 0 ,,,,,
Lateral Weir SS=0.05,0.05,
Lateral Weir Type= 0
Lateral Weir Connection Pos and Dist= 0 ,1
Lateral Weir SE= 2
       0     -.1     198     -.7
Lateral Weir HW RS Station=800.*   ,-1
Lateral Weir TW RS Station=800.*   ,-1
LW Div RC= 0 ,False,

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
Type RM Length L Ch R = 6 ,699     ,,,
Lateral Weir Pos= 0
Lateral Weir End=threeRivers     ,left            ,700.*   ,
Lateral Weir Distance=1
Lateral Weir TW Multiple XS=-1
Lateral Weir WD=1
Lateral Weir Coef=1.1
Lateral Weir WSCriteria=-1
Lateral Weir Flap Gates= 0
Lateral Weir Hagers EQN= 0 ,,,,,
Lateral Weir SS=0.05,0.05,
Lateral Weir Type= 0
Lateral Weir Connection Pos and Dist= 0 ,1
Lateral Weir SE= 2
       0     -.4     198      -1
Lateral Weir HW RS Station=700.*   ,-1
Lateral Weir TW RS Station=700.*   ,-1
LW Div RC= 0 ,False,

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
Type RM Length L Ch R = 1 ,0       ,0,0,0
#Sta/Elev= 3
       0   -2.99      10      -3      20   -2.99
#Mann= 3 , 0 , 0
       0     .03       0       0     .03       0      20     .03       0
Bank Sta=0,20
XS Rating Curve= 0 ,0
Exp/Cntr=0.3,0.1

Chan Stop Cuts=-1
Use User Specified Reach Order=0
Composite Channel Slope=5