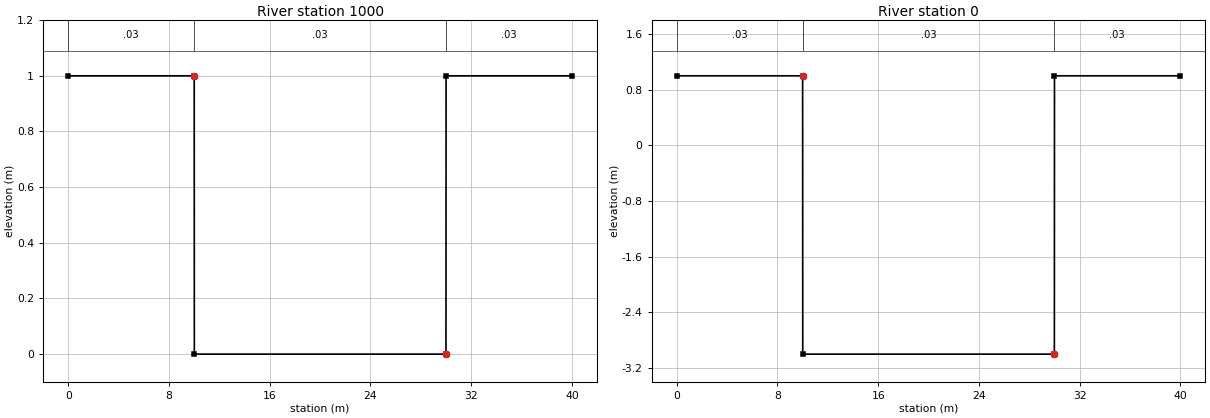
--- IdealBackwater.prj (project) ---

Proj Title=IdealBackwater
Current Plan=p01
Default Exp/Contr=0.3,0.1
SI Units
Geom File=g01
Unsteady File=u01
Plan File=p01
Y Axis Title=Elevation
X Axis Title(PF)=Main Channel Distance
X Axis Title(XS)=Station
BEGIN DESCRIPTION:
END DESCRIPTION:
DSS Start Date=22SEP2008
DSS Start Time=00:00
DSS End Date=22SEP2008
DSS End Time=09:00
DSS File=dss
DSS Export Rating Curves= 0
DSS Export Rating Curve Sorted= 0
DSS Export Volume Flow Curves= 0
DXF OffsetX= 0
DXF OffsetY= 0
DXF ScaleX= 1
DXF ScaleY= 10

--- IdealBackwater.p01 (plan) ---

Plan Title=IdealBackwater
Program Version=4.10
Short Identifier=IdealBackwater
Simulation Date=22SEP2008,00:00,22SEP2008,09:00
Geom File=g01
Flow File=u01
Subcritical Flow
K Sum by GR= 0
Std Step Tol= 0.003
Critical Tol= 0.003
Num of Std Step Trials= 20
Max Error Tol= 0.1
Flow Tol Ratio= 0.001
Split Flow NTrial= 30
Split Flow Tol= 0.006
Split Flow Ratio= 0.02
Log Output Level= 0
Friction Slope Method= 1
Unsteady Friction Slope Method= 2
Unsteady Bridges Friction Slope Method= 1
Parabolic Critical Depth
Global Vel Dist= 0 , 0 , 0
Global Log Level= 0
CheckData=True
Encroach Param=-1 ,0,0, 0
Computation Interval=3SEC
Output Interval=1MIN
Run HTab= 1
Run UNet= 1
Run PostProcess= 1
Run WQNet= 0
UNET Theta= 0.6
UNET Theta Warmup= 1
UNET ZTol= 0.001
UNET ZSATol= 0.015
UNET MxIter= 20
UNET MaxInSteps= 0
UNET DtIC= 0
UNET DtMin= 0
UNET MaxCRTS= 20
UNET WFStab= 2
UNET SFStab= 1
UNET WFX= 1
UNET SFX= 1
UNET DSS MLevel= 4
UNET DZMax Abort= 30
UNET Convert EG Bridges= 0
UNET Use Existing IB Tables=-1
UNET Froude Reduction=True
UNET Froude Limit= 1
UNET Froude Power= 128
UNET Time Slicing=0,0, 5
UNET Junction Losses=0
Instantaneous Interval=1MIN
DSS File=dss
Write IC File= 0
Write IC File at Sim End=0
Echo Input=False
Echo Parameters=False
Echo Output=False
Write Detailed= 0
Stage Flow Hydrograph=RIVER1          ,REACH1          ,1000
Stage Flow Hydrograph=RIVER1          ,REACH1          ,980.*
Stage Flow Hydrograph=RIVER1          ,REACH1          ,960.*
Stage Flow Hydrograph=RIVER1          ,REACH1          ,940.*
Stage Flow Hydrograph=RIVER1          ,REACH1          ,920.*
Stage Flow Hydrograph=RIVER1          ,REACH1          ,900.*
Stage Flow Hydrograph=RIVER1          ,REACH1          ,880.*
Stage Flow Hydrograph=RIVER1          ,REACH1          ,860.*
Stage Flow Hydrograph=RIVER1          ,REACH1          ,840.*
Stage Flow Hydrograph=RIVER1          ,REACH1          ,820.*
Stage Flow Hydrograph=RIVER1          ,REACH1          ,800.*
Stage Flow Hydrograph=RIVER1          ,REACH1          ,780.*
Stage Flow Hydrograph=RIVER1          ,REACH1          ,760.*
Stage Flow Hydrograph=RIVER1          ,REACH1          ,740.*
Stage Flow Hydrograph=RIVER1          ,REACH1          ,720.*
Stage Flow Hydrograph=RIVER1          ,REACH1          ,700.*
Stage Flow Hydrograph=RIVER1          ,REACH1          ,680.*
Stage Flow Hydrograph=RIVER1          ,REACH1          ,660.*
Stage Flow Hydrograph=RIVER1          ,REACH1          ,640.*
Stage Flow Hydrograph=RIVER1          ,REACH1          ,620.*
Stage Flow Hydrograph=RIVER1          ,REACH1          ,600.*
Stage Flow Hydrograph=RIVER1          ,REACH1          ,580.*
Stage Flow Hydrograph=RIVER1          ,REACH1          ,560.*
Stage Flow Hydrograph=RIVER1          ,REACH1          ,540.*
Stage Flow Hydrograph=RIVER1          ,REACH1          ,520.*
Stage Flow Hydrograph=RIVER1          ,REACH1          ,500.*
Stage Flow Hydrograph=RIVER1          ,REACH1          ,480.*
Stage Flow Hydrograph=RIVER1          ,REACH1          ,460.*
Stage Flow Hydrograph=RIVER1          ,REACH1          ,440.*
Stage Flow Hydrograph=RIVER1          ,REACH1          ,420.*
Stage Flow Hydrograph=RIVER1          ,REACH1          ,400.*
Stage Flow Hydrograph=RIVER1          ,REACH1          ,380.*
Stage Flow Hydrograph=RIVER1          ,REACH1          ,360.*
Stage Flow Hydrograph=RIVER1          ,REACH1          ,340.*
Stage Flow Hydrograph=RIVER1          ,REACH1          ,320.*
Stage Flow Hydrograph=RIVER1          ,REACH1          ,300.*
Stage Flow Hydrograph=RIVER1          ,REACH1          ,280.*
Stage Flow Hydrograph=RIVER1          ,REACH1          ,260.*
Stage Flow Hydrograph=RIVER1          ,REACH1          ,240.*
Stage Flow Hydrograph=RIVER1          ,REACH1          ,220.*
Stage Flow Hydrograph=RIVER1          ,REACH1          ,200.*
Stage Flow Hydrograph=RIVER1          ,REACH1          ,180.*
Stage Flow Hydrograph=RIVER1          ,REACH1          ,160.*
Stage Flow Hydrograph=RIVER1          ,REACH1          ,140.*
Stage Flow Hydrograph=RIVER1          ,REACH1          ,120.*
Stage Flow Hydrograph=RIVER1          ,REACH1          ,100.*
Stage Flow Hydrograph=RIVER1          ,REACH1          ,79.9999*
Stage Flow Hydrograph=RIVER1          ,REACH1          ,60.*
Stage Flow Hydrograph=RIVER1          ,REACH1          ,40.0000*
Stage Flow Hydrograph=RIVER1          ,REACH1          ,19.9999*
Stage Flow Hydrograph=RIVER1          ,REACH1          ,0
WQ AD Non Conservative
WQ ULTIMATE=-1
WQ Max Comp Step=1HOUR
WQ Output Interval=15MIN
WQ Output Selected Increments= 0
WQ Output face flow=0
WQ Output face velocity=0
WQ Output face area=0
WQ Output face dispersion=0
WQ Output cell volume=0
WQ Output cell surface area=0
WQ Output cell continuity=0
WQ Output cumulative cell continuity=0
WQ Output face conc=0
WQ Output face dconc_dx=0
WQ Output face courant=0
WQ Output face peclet=0
WQ Output face adv mass=0
WQ Output face disp mass=0
WQ Output cell mass=0
WQ Output cell source sink temp=0
WQ Output cell source sink nsm=0
WQ Output MaxMinRange=-1
WQ Daily Max Min Mean=-1
WQ Daily Range=0
WQ Daily Time=0
WQ Create Restart=0
WQ Fixed Restart=0
WQ System Summary=0
WQ Use Fixed Temperature=0
Sorting and Armoring Iterations= 10
XS Update Threshold= 0.02
Hydraulics Update Threshold= 0.02
Energy Slope Method= 1
Volume Change Method= 0
XS Weighting Method= 0
Number of US Weighted Cross Sections= 1
Number of DS Weighted Cross Sections= 1
Upstream XS Weight=0.25
Main XS Weight=0.5
Downstream XS Weight=0.25
Number of DS XS's Weighted with US Boundary= 1
Upstream Boundary Weight= 1
Weight of XSs Associated with US Boundary= 0
Number of US XS's Weighted with DS Boundary= 1
Downstream Boundary Weight= 0.5
Weight of XSs Associated with DS Boundary= 0.5
Sediment Output Level= 4
Mass or Volume Output= 0
Output Increment Type= 1
Profile and TS Output Increment= 10
XS Output Flag= 0
XS Output Increment= 10
Disregard all LS=0
Disregard all Conn=0
Disregard all Breaches=0
Disregard all Pumps=0

--- IdealBackwater.u01 (unsteady flow) ---

Flow Title=IdealBackwater
Program Version=4.10
Use Restart= 0
Boundary Location=RIVER1          ,REACH1          ,1000    ,        ,                ,                ,
Interval=1HOUR
Flow Hydrograph= 14
       0       0       0       0       0       0       0       0       0       0
       0       0       0       0
Use DSS=False
CWMS InputPosition= 0
Use Fixed Start Time=False
Is Critical Boundary=False
Boundary Location=RIVER1          ,REACH1          ,0       ,        ,                ,                ,
Interval=1MIN
Stage Hydrograph= 752
      .7.7623735 .822021.8763356.9229435.9598076.9853169.9983566.9983566.9853169
.9598076.9229435.8763356 .822021.7623735      .7.6376265 .577979.5236644.4770566
.4401924 .414683.4016434.4016434 .414683.4401924.4770566.5236644 .577979.6376265
      .7.7623735 .822021.8763356.9229435.9598076.9853169.9983566.9983566.9853169
.9598076.9229435.8763356 .822021.7623735      .7.6376265 .577979.5236644.4770566
.4401924 .414683.4016434.4016434 .414683.4401924.4770566.5236644 .577979.6376265
      .7.7623735 .822021.8763356.9229435.9598076.9853169.9983566.9983566.9853169
.9598076.9229435.8763356 .822021.7623735      .7.6376265 .577979.5236644.4770566
.4401924 .414683.4016434.4016434 .414683.4401924.4770566.5236644 .577979.6376265
      .7.7623735 .822021.8763356.9229435.9598076.9853169.9983566.9983566.9853169
.9598076.9229435.8763356 .822021.7623735      .7.6376265 .577979.5236644.4770566
.4401924 .414683.4016434.4016434 .414683.4401924.4770566.5236644 .577979.6376265
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Use DSS=False
CWMS InputPosition= 0
Use Fixed Start Time=False
Is Critical Boundary=False

--- IdealBackwater.g01 (geometry) ---

Geom Title=IdealBackwater
Program Version=4.10

River Reach=RIVER1          ,REACH1
Reach XY= 2
0.336909871244640.879828326180260.360515021459230.17381974248927

Type RM Length L Ch R = 1 ,1000    ,20,20,20
#Sta/Elev= 6
       0       1      10       1   10.01       0      30       0   30.01       1
      40       1
#Mann= 3 , 0 , 0
       0     .03       0      10     .03       0      30     .03       0
Bank Sta=10,30
XS Rating Curve= 0 ,0
Exp/Cntr=0.3,0.1

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
Type RM Length L Ch R = 1 ,0       ,0,0,0
#Sta/Elev= 6
       0       1      10       1   10.01      -3      30      -3   30.01       1
      40       1
#Mann= 3 , 0 , 0
       0     .03       0      10     .03       0      30     .03       0
Bank Sta=10,30
XS Rating Curve= 0 ,0
Exp/Cntr=0.3,0.1

Chan Stop Cuts=-1
Use User Specified Reach Order=0
Composite Channel Slope=5